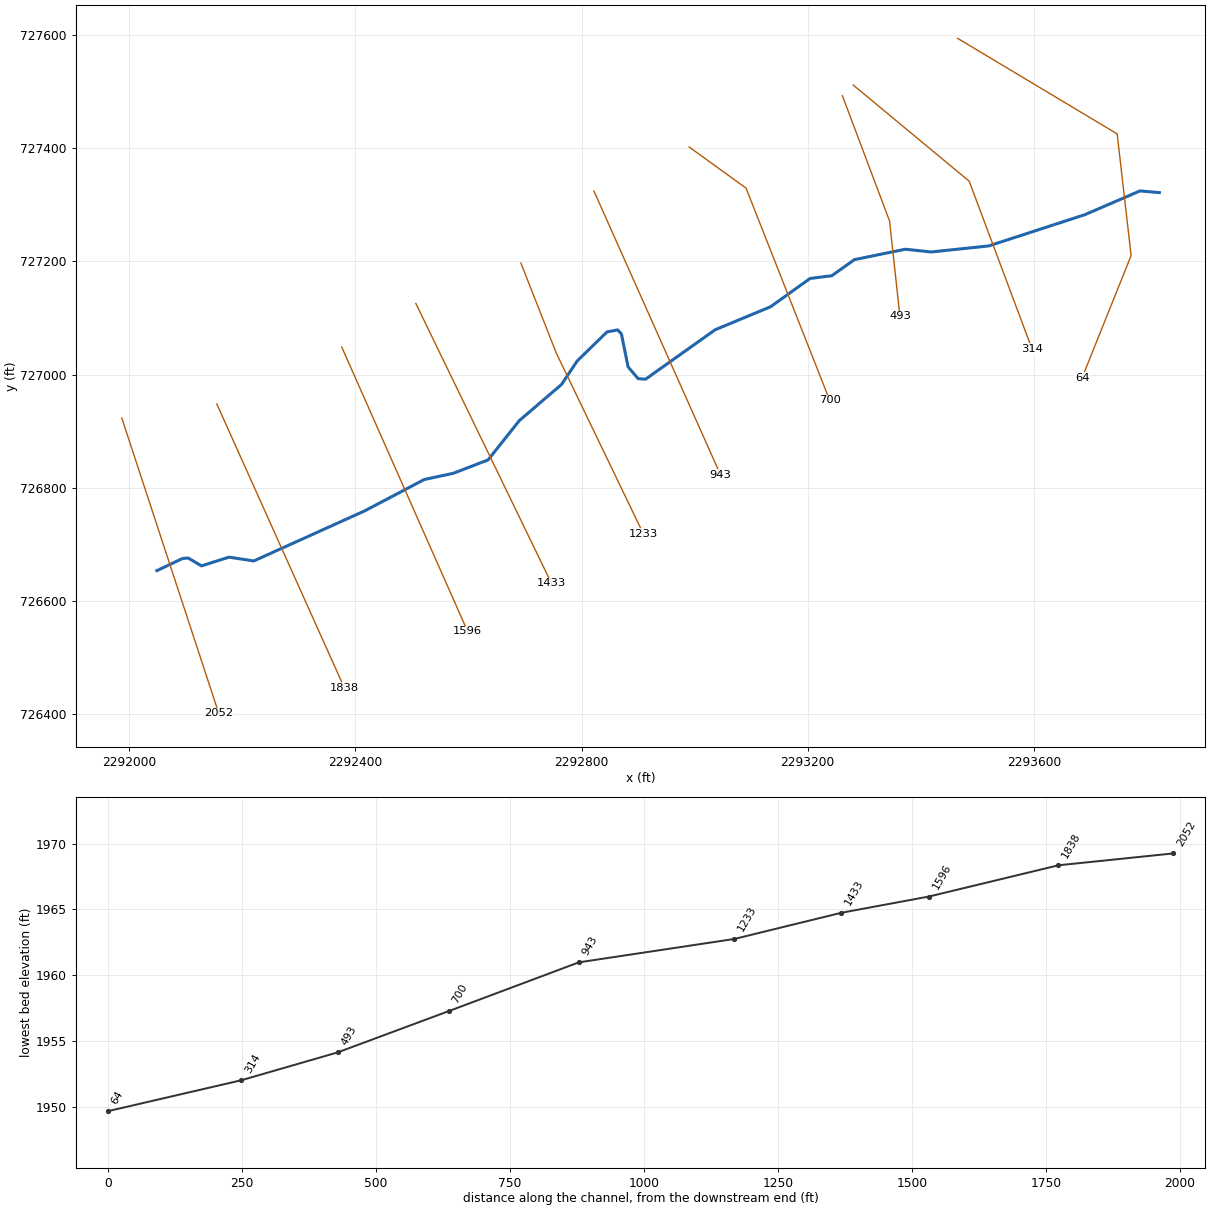
--- PEARCYRNT1.prj (project) ---

Proj Title=PEARCYRNT1
Current Plan=p01
Default Exp/Contr=0,0
English Units
Geom File=g01
Flow File=f01
Plan File=p01
BEGIN DESCRIPTION:
----------MODEL BY WOOD PLC 2022----------
AFH study
Randolph County, WV
HEC-RAS Version: RAS 6.2
Vertical Datum: NAVD88
Projection: NAD 1983 StatePlane West Virginia S FIPS 4702 (US Feet)
Terrain: 1-meter LIDAR (FEMA Region III 3DEP collected 2016-2018)
Land Use: 2019 NLCD
Hydrologic Method:
WV SIR2010-5033 regression equations
Additional Model Notes:
None
END DESCRIPTION:
DSS Export Rating Curves= 0
DSS Export Rating Curve Sorted= 0
DSS Export Volume Flow Curves= 0
DXF OffsetX= 0
DXF OffsetY= 0
DXF ScaleX= 0
DXF ScaleY= 0

--- PEARCYRNT1.p01 (plan) ---

Plan Title=Floodplain
Program Version=6.20
Short Identifier=Floodplain
Geom File=g01
Flow File=f01
Subcritical Flow
K Sum by GR= 0
Std Step Tol= 0.01
Critical Tol= 0.01
Num of Std Step Trials= 20
Max Error Tol= 0.3
Flow Tol Ratio= 0.001
Split Flow NTrial= 30
Split Flow Tol= 0.02
Split Flow Ratio= 0.02
Log Output Level= 0
Friction Slope Method= 1
Unsteady Friction Slope Method= 2
Unsteady Bridges Friction Slope Method= 1
Parabolic Critical Depth
Global Vel Dist= 0 , 0 , 0
Global Log Level= 0
CheckData=True
Encroach Param=-1 ,0,0, 0
Mapping Interval=1HOUR
Computation Time Step Use Courant=        0
Computation Time Step Use Time Series=    0
Computation Time Step Count To Double=0
Computation Time Step Max Doubling=0
Computation Time Step Max Halving=0
Computation Time Step Residence Courant=0
Run HTab= 0
Run UNet= 0
Run Sediment= 0
Run PostProcess= 0
Run WQNet= 0
Run RASMapper=-1
UNET Theta= 0
UNET Theta Warmup= 0
UNET ZTol= 0
UNET ZSATol= 0
UNET MxIter= 0
UNET Max Iter WO Improvement= 0
UNET MaxInSteps= 0
UNET DtIC= 0
UNET DtMin= 0
UNET MaxCRTS= 0
UNET WFStab= 0
UNET SFStab= 0
UNET WFX= 1
UNET SFX= 1
UNET Gravity=32.174
UNET 1D Methodology=Finite Difference
UNET DSS MLevel= 1
UNET Pardiso=0
UNET DZMax Abort= 0
UNET Use Existing IB Tables= 0
UNET Froude Reduction=False
UNET Froude Limit= 0
UNET Froude Power= 0
UNET D1 Cores= 0
UNET WindReference=Eulerian
UNET WindDragFormulation=Hsu (1988)
UNET D2 Coriolis=0
UNET D2 Cores= 0
UNET D2 Theta= 1
UNET D2 Theta Warmup= 1
UNET D2 Z Tol= 0.01
UNET D2 Volume Tol= 0.01
UNET D2 Max Iterations= 20
UNET D2 Equation= 0
UNET D2 RampUpFraction=0.1
UNET D2 TimeSlices= 1
UNET D2 Turbulence Formulation=Non-Conservative (original)
UNET D2 Eddy Viscosity=0.3
UNET D2 Transverse Eddy Viscosity=0.1
UNET D2 Smagorinsky Mixing=0
UNET D2 BCVolumeCheck=0
UNET D2 Cores=0
UNET D2 SolverType=PARDISO (Direct)
UNET D2 Minimum Iterations= 2147483647
UNET D2 Maximum Iterations= 2147483647
UNET D2 Restart Number= 10
UNET D2 Relaxation Coeff=1.3
UNET D2 SOR Precondition Iterations= 10
UNET D2 ILUT Maximum Fill= 8
UNET D2 ILUT Tolerance=1E-08
UNET D1D2 MaxIter= 0
UNET D1D2 ZTol=0.01
UNET D1D2 QTol=0.1
UNET D1D2 MinQTol=1
Write IC File= 0
Write IC File at Fixed DateTime=0
Write IC File at Sim End=0
Echo Input=False
Echo Parameters=False
Echo Output=False
Write Detailed= 0
HDF Write Warmup=0
HDF Write Time Slices=0
HDF Flush=0
HDF Compression= 1
HDF Chunk Size= 1
HDF Spatial Parts= 1
HDF Use Max Rows=0
HDF Fixed Rows= 1
Calibration Method= 0
Calibration Iterations= 20
Calibration Max Change=0.05
Calibration Tolerance=0.2
Calibration Maximum=1.5
Calibration Minimum=0.5
Calibration Optimization Method= 1
WQ AD Non Conservative
WQ ULTIMATE=-1
WQ Max Comp Step=1HOUR
WQ Output Interval=15MIN
WQ Output Selected Increments= 0
WQ Output face flow=0
WQ Output face velocity=0
WQ Output face area=0
WQ Output face dispersion=0
WQ Output cell volume=0
WQ Output cell surface area=0
WQ Output cell continuity=0
WQ Output cumulative cell continuity=0
WQ Output face conc=0
WQ Output face dconc_dx=0
WQ Output face courant=0
WQ Output face peclet=0
WQ Output face adv mass=0
WQ Output face disp mass=0
WQ Output cell mass=0
WQ Output cell source sink temp=0
WQ Output nsm pathways=0
WQ Output nsm derived pathways=0
WQ Create Restart=0
WQ Fixed Restart=0
WQ System Summary=0
WQ Write To DSS=0
Sorting and Armoring Iterations= 10
XS Update Threshold= 0.02
Bed Roughness Predictor= 0
Hydraulics Update Threshold= 0.02
Energy Slope Method= 1
Volume Change Method= 1
Sediment Retention Method= 0
Sediment TS Multiplier= 1
Warm Up Method= 0
XS Weighting Method= 0
Number of US Weighted Cross Sections= 1
Number of DS Weighted Cross Sections= 1
Upstream XS Weight=0
Main XS Weight=1
Downstream XS Weight=0
Number of DS XS's Weighted with US Boundary= 1
Upstream Boundary Weight= 1
Weight of XSs Associated with US Boundary= 0
Number of US XS's Weighted with DS Boundary= 1
Downstream Boundary Weight= 0.5
Weight of XSs Associated with DS Boundary= 0.5
Percentile Method= 0
Sediment Output Level= 3
Mass or Volume Output= 0
Output Increment Type= 1
Profile and TS Output Increment= 1
Transport Output Increment 1
XS Output Flag= 0
XS Output Increment= 10
Read HDF5 Sediment Hotstart= 0
Sediment Hotstart Type= 0
Write Gradation File= 0
Read Gradation Hotstart= 0
Write HDF5 File= 1
Write Binary Output= 1
Write DSS Sediment File= 0
DSS Sediment Output Type= 1
SV Curve= 0
Specific Gage Flag= 0
Subcell Erosion Methods= 0
Subcell Deposition Methods= 0
Advection Scheme= 1
Matrix Solver= 0
Implicit Weighting Factor= 1
Maximum Outer Loop Convergence Iterations= 5
Convergence Maximum Absolute= 0.001
Convergence RMSE= 0.0001
Grain Fractions Max Abs Error= 0.001
Max Subgrid Regions= 1
Max Subgrid Length Scale= 3.402823E+38
Initial Layer Thickness= 3.402823E+38
Min Layer Thickness= 3.402823E+38
Max Layer Thickness= 3.402823E+38
Number of Layers= 5

--- PEARCYRNT1.f01 (steady flow) ---

Flow Title=Flow
Program Version=6.20
Number of Profiles= 1
Profile Names=P100yr
River Rch & RM=PEARCYRNT1,Main,2052
     348
Boundary for River Rch & Prof#=PEARCYRNT1,Main            , 1
Up Type= 0
Dn Type= 3
Dn Slope=0.00954
DSS Import GetInterval= 0
DSS Import GetPeak= 0
DSS Import FillOption= 0

--- PEARCYRNT1.g01 (geometry) ---

Geom Title=Geometry
Program Version=6.10

River Reach=PEARCYRNT1      ,Main
Reach XY= 30
2292048.95479958726653.3015793262292094.29610443 726674.72625865
 2292104.3289701726675.681769669    2292127.8203726661.672517523
2292176.47005178 726677.115036192292220.42355849726670.426459074
2292416.31900004726758.8620000032292521.87499999726814.417000011
     2292573.611726825.5289999992292634.72200003726849.140000001
2292689.93100002726918.584000006     2292764.583 726982.47300002
2292792.36100003727024.1400000162292845.13900001727075.528999999
     2292863.889727079.0010000022292870.48600003727072.055999994
2292882.29200001727013.723000005        2292900.726992.890000001
2292913.19400001726991.8480000052293036.45800003727079.348000005
     2293134.375 727119.973000022293204.16699998727169.973000005
2293242.70800002727174.8340000062293282.63900003727203.306000009
2293372.56900004727221.709000021     2293418.403 727216.84800002
     2293520.052727227.525000006     2293690.506727282.929000005
2293787.59800003727324.8120000062293821.85849756727321.857880751

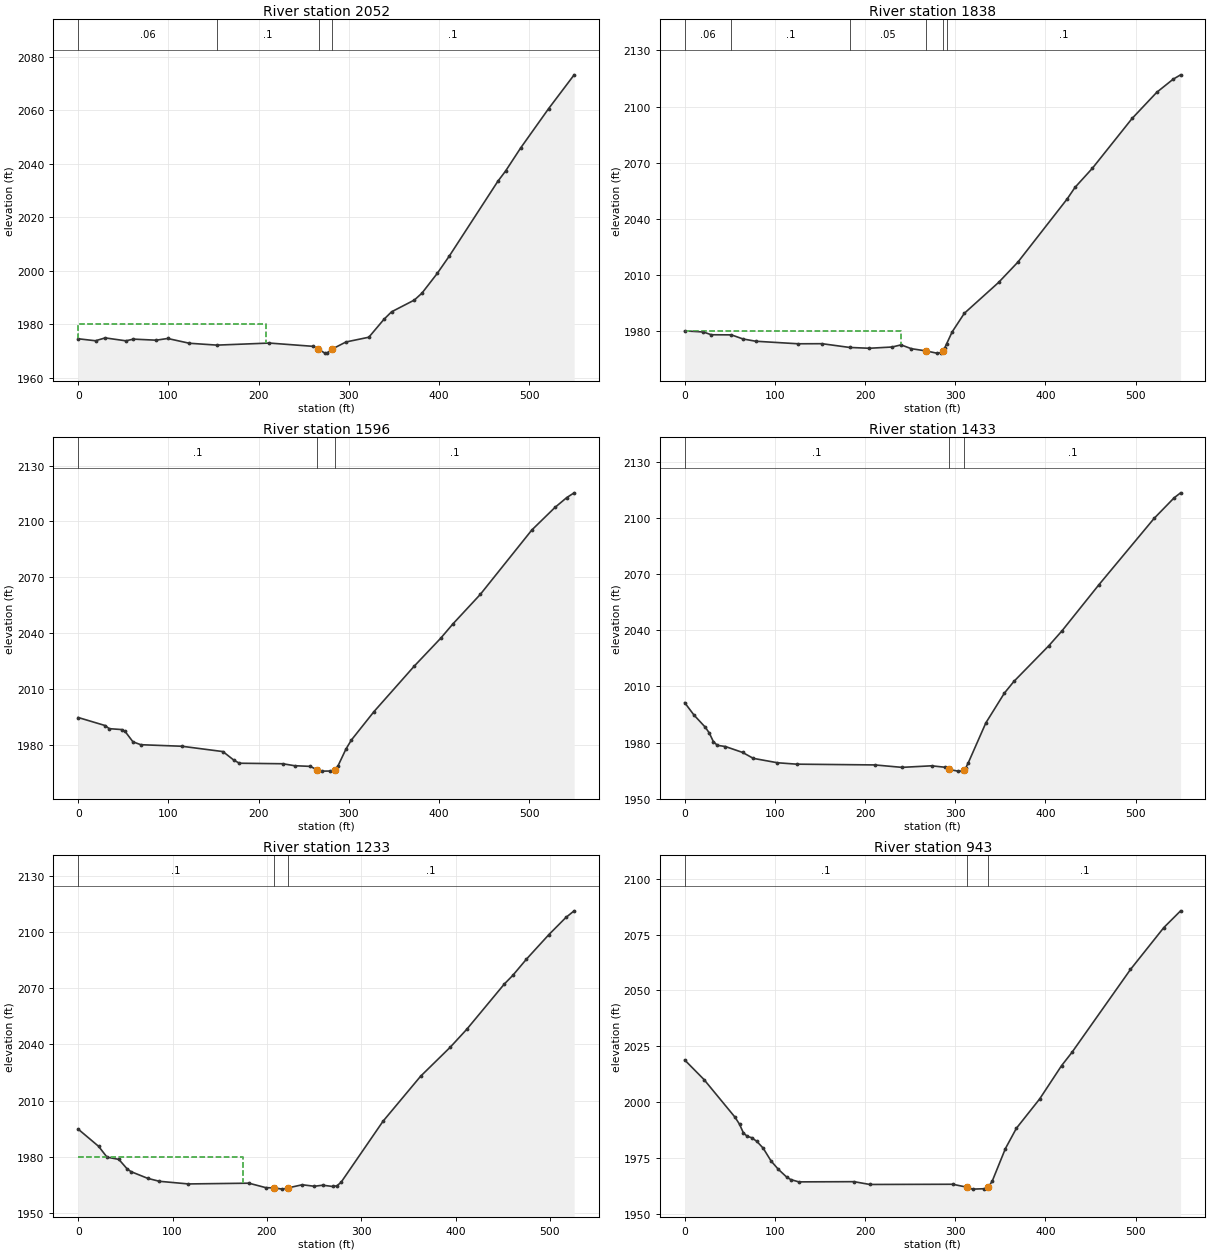
Type RM Length L Ch R = 1 ,2052    ,214.4,214.4,214.4
XS GIS Cut Line= 2
2291986.84635011726923.3826823692292158.42670539 726400.83107565
#Sta/Elev= 30
       0 1974.61    19.2 1973.87    29.9 1974.94    52.8 1973.85    61.3 1974.48
    86.5 1974.08    99.2 1974.72   123.2 1972.94   153.9 1972.24     212 1973.01
   260.7 1971.78   265.9  1970.9   266.51970.717   273.5 1969.25     276 1969.27
   281.41970.718   281.7 1970.79     297 1973.42   322.3 1975.19   339.1 1981.89
   347.5 1984.68   372.8 1989.08   381.2 1991.65   398.1 1998.99   411.7 2005.59
   465.4 2033.45   473.9 2037.23   490.7 2045.89   521.6 2060.53     550 2073.19
#Mann= 4 ,-1,0
       0     .06       0   153.9      .1       0   266.5    .045       0
   281.4      .1       0
#XS Ineff= 2 , 0
          208.61    1980
Permanent Ineff=
       F       F
Bank Sta=265.9,281.7
XS Rating Curve= 0 ,0
Exp/Cntr(USF)=0,0
Exp/Cntr=0.3,0.1

Type RM Length L Ch R = 1 ,1838    ,241.6,241.6,241.6
XS GIS Cut Line= 2
2292154.91903754726948.0869958242292380.31444956726446.392957353
#Sta/Elev= 30
       0 1980.23    20.7 1979.65    29.5 1978.16    51.9  1978.1    64.6 1975.92
    78.8  1974.7     126 1973.34   152.3 1973.39     183 1971.38   204.9 1970.95
   230.1 1971.62     240 1972.76   251.3 1970.73   267.3 1969.55   279.5 1968.35
   283.8 1968.54     2861969.619   288.2 1970.91   290.6 1973.43   296.6 1979.66
   310.1  1989.6   348.1 2006.09   369.6 2016.99   424.2  2050.7   432.9 2056.87
   452.1 2067.04   496.3 2093.73   523.6 2107.66   541.7 2114.63     550 2116.97
#Mann= 6 ,-1,0
       0     .06       0    51.9      .1       0     183     .05       0
   267.3    .045       0     286     .05       0   290.6      .1       0
#XS Ineff= 2 , 0
             240    1980
Permanent Ineff=
       F       F
Bank Sta=267.3,286
XS Rating Curve= 0 ,0
Exp/Cntr(USF)=0,0
Exp/Cntr=0.3,0.1

Type RM Length L Ch R = 1 ,1596    ,163.2,163.2,163.2
XS GIS Cut Line= 2
2292375.92958566727048.6493027712292598.55872906726545.721609652
#Sta/Elev= 30
       0 1994.76    29.9 1990.44    34.4 1988.77    48.3 1988.29    51.9 1987.34
    60.7 1981.72    69.4 1980.16     115 1979.33   160.5 1976.47   172.6 1971.88
   178.8 1970.22   226.9 1969.94     240 1968.88   257.5 1968.53     2651966.615
   270.6 1965.98   279.4 1966.03   284.4  1966.6   288.1 1968.78   296.9 1977.81
     303 1982.71   328.1 1997.98   372.7 2022.36   401.9 2037.26   415.6 2045.03
   445.9 2060.83   503.1 2095.43   528.7 2107.51   541.8 2112.81     550 2115.36
#Mann= 3 ,-1,0
       0      .1       0     265    .045       0   284.4      .1       0
Bank Sta=265,284.4
XS Rating Curve= 0 ,0
Exp/Cntr(USF)=0,0
Exp/Cntr=0.3,0.1

Type RM Length L Ch R = 1 ,1433    ,200.1,200.1,200.1
XS GIS Cut Line= 2
2292506.98024149727125.7764415742292746.81568311726630.822947856
#Sta/Elev= 30
       0 2001.32    10.3 1994.71    22.9 1988.18    27.3  1985.1    31.8 1980.53
    36.2 1978.53    45.1 1977.89    64.2 1974.74    76.1 1971.57   102.9 1969.22
   124.1 1968.47   210.9 1968.06   240.9 1966.76   273.8 1967.59   288.8 1966.82
   293.11965.682   302.9 1964.75   307.4 1964.81   309.7 1965.57   311.8 1966.57
   314.6 1969.28     334 1990.51   354.6 2006.44   365.1 2012.65     404  2031.8
   418.5  2039.7   459.4  2064.3   520.7 2099.77   542.9 2110.75     550 2113.37
#Mann= 3 ,-1,0
       0      .1       0   293.1    .045       0   309.7      .1       0
Bank Sta=293.1,309.7
XS Rating Curve= 0 ,0
Exp/Cntr(USF)=0,0
Exp/Cntr=0.3,0.1

Type RM Length L Ch R = 1 ,1233    ,289.7,289.7,289.7
XS GIS Cut Line= 3
2292692.72986351727197.2403348452292755.32493172727038.144536473
2292909.20447441726718.648875808
#Sta/Elev= 30
       0 1994.77    21.6 1985.61    30.5 1979.84    43.1 1978.62    51.6 1973.71
    55.9  1972.1    73.7 1968.51      86 1966.94   116.8 1965.53   180.9 1965.93
   198.7 1963.56   207.6  1963.4   216.4 1962.76   222.6 1963.44   237.5 1965.09
   250.2 1964.29   259.2 1964.85   269.7 1964.17   274.2 1964.53   278.6 1966.43
     323 1998.97   362.9 2023.03   394.2 2038.47   411.8 2048.08   451.7  2072.3
   460.6 2076.87     475 2085.49   498.9 2098.66   516.9 2107.78   525.6 2111.31
#Mann= 3 ,-1,0
       0      .1       0   207.6    .045       0   222.6      .1       0
#XS Ineff= 2 , 0
             175    1980
Permanent Ineff=
       F       F
Bank Sta=207.6,222.6
XS Rating Curve= 0 ,0
Exp/Cntr(USF)=0,0
Exp/Cntr=0.3,0.1

Type RM Length L Ch R = 1 ,943     ,242.8,242.8,242.8
XS GIS Cut Line= 2
2292821.87185718 727324.691465492293045.93104385726822.399238924
#Sta/Elev= 30
       0 2018.85    21.4  2010.1    55.9 1993.17    60.8 1990.07    65.2 1986.12
    69.5 1984.62    74.4 1984.02    80.1 1982.36    87.1 1979.32    95.8 1973.61
   103.8 1969.89   113.4 1966.28   117.7 1965.27   126.5 1964.24   187.8 1964.33
   205.3 1963.08   297.3 1963.17   313.3 1961.82   319.2 1960.99   332.3 1961.17
   336.7 1961.82   341.1  1964.6   355.7 1979.17   367.9 1988.27   393.7 2001.41
     418 2016.32   429.4 2022.21   494.4 2059.41   531.4 2078.18     550 2085.67
#Mann= 3 ,-1,0
       0      .1       0   313.3    .045       0   336.7      .1       0
Bank Sta=313.3,336.7
XS Rating Curve= 0 ,0
Exp/Cntr(USF)=0,0
Exp/Cntr=0.3,0.1

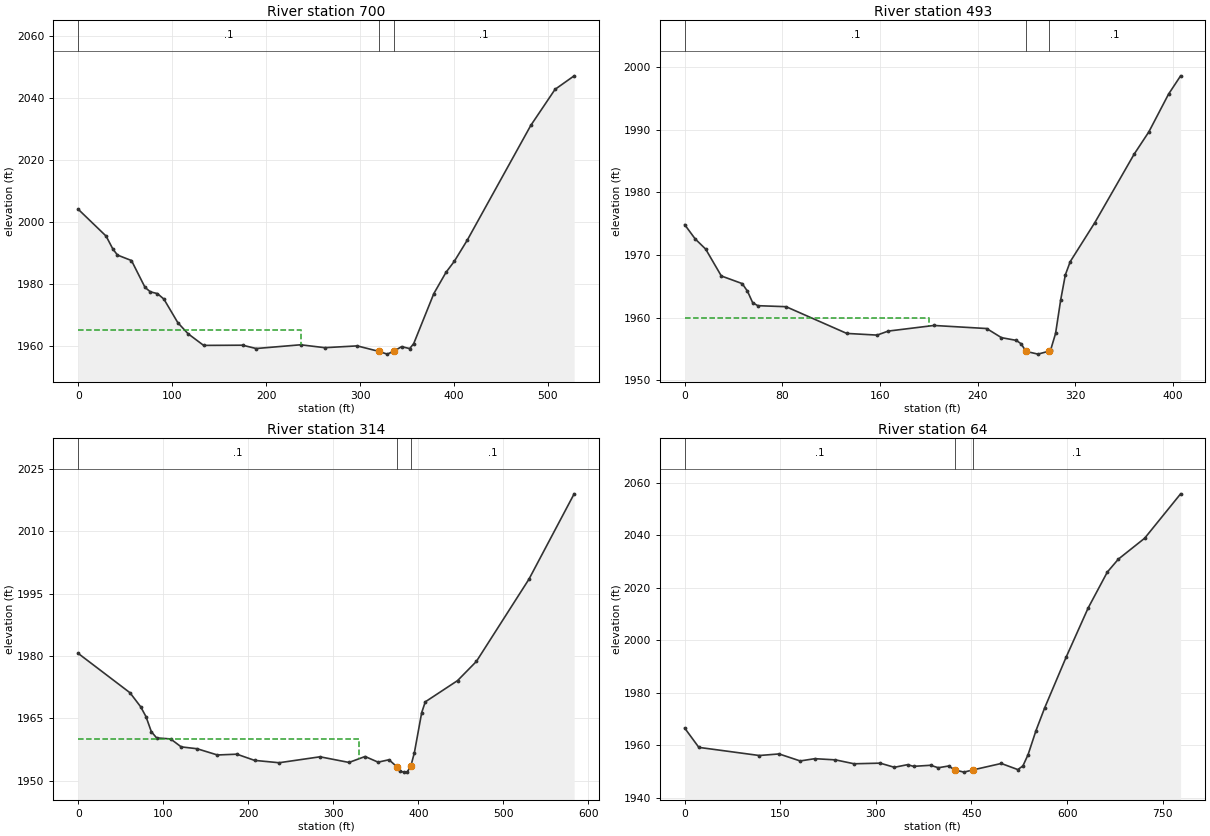
Type RM Length L Ch R = 1 ,700     ,207.2,207.2,207.2
XS GIS Cut Line= 3
2292990.27585323727402.5785101332293090.97854335727329.721167372
2293238.95900017726954.289267651
#Sta/Elev= 30
       0 2004.09    29.7 1995.41    36.9 1991.23    41.8 1989.29    56.7 1987.52
    71.1 1978.86    76.8 1977.41    84.3 1976.84    91.2 1975.07     106 1967.46
   116.9 1963.88   133.5 1960.11     175 1960.17   189.4  1959.1   236.7 1960.31
   262.5 1959.37   296.9 1959.95   319.7  1958.2   328.9 1957.29   335.71958.203
   344.2 1959.71   352.8 1959.08   357.1  1960.7   378.5 1976.85   391.4 1983.69
   400.3 1987.28   414.1 1994.12   481.7 2031.18   507.5 2042.82527.8384 2047.19
#Mann= 3 ,-1,0
       0      .1       0   319.7    .045       0   335.7      .1       0
#XS Ineff= 2 , 0
        237.6462    1965
Permanent Ineff=
       F       F
Bank Sta=319.7,335.7
XS Rating Curve= 0 ,0
Exp/Cntr(USF)=0,0
Exp/Cntr=0.3,0.1

Type RM Length L Ch R = 1 ,493     ,179.5,179.5,179.5
XS GIS Cut Line= 3
 2293261.3017331 727493.262844932293344.76182405727271.571978347
2293363.01871895727103.347732527
#Sta/Elev= 30
       0 1974.85     8.6 1972.57    17.2 1970.94      30 1966.65    47.1 1965.43
    51.4 1964.22    55.7 1962.37    59.9  1961.9      83 1961.74   132.7 1957.47
   157.6  1957.2   166.6 1957.84   204.1 1958.74   247.3 1958.25   259.4 1956.79
   271.5 1956.36   275.5 1955.81   279.5  1954.6   289.3 1954.16   298.6 1954.65
   299.6 1954.78   303.7 1957.46   307.9 1962.83   311.7 1966.82   315.7 1968.94
   335.9 1975.19     368  1986.1   380.1 1989.68   396.2  1995.7   406.1 1998.63
#Mann= 3 ,-1,0
       0      .1       0   279.5    .045       0   298.6      .1       0
#XS Ineff= 2 , 0
             200    1960
Permanent Ineff=
       F       F
Bank Sta=279.5,298.6
XS Rating Curve= 0 ,0
Exp/Cntr(USF)=0,0
Exp/Cntr=0.3,0.1

Type RM Length L Ch R = 1 ,314     ,249.4,249.4,249.4
XS GIS Cut Line= 3
2293280.53763658727512.0556635262293485.60072753727341.991430085
2293596.74274142727045.247431276
#Sta/Elev= 30
       0 1980.63    60.9 1971.16    73.4  1967.8    79.7 1965.42      86 1961.79
    92.2 1960.29   108.7 1960.04   121.1 1958.13   139.8 1957.68   163.7 1956.18
   186.6 1956.37   207.4 1954.88   236.3 1954.31   284.4 1955.74   318.5 1954.38
   337.4 1955.81   352.7 1954.45   365.5 1955.03   374.7 1953.36   378.3 1952.29
   382.6 1952.05   386.9  1952.1   391.1 1953.42   395.4 1956.75     404 1966.39
   408.2 1968.97   446.2 1974.09   468.3  1978.7   530.1 1998.49   583.3 2019.05
#Mann= 3 ,-1,0
       0      .1       0   374.7    .045       0   391.1      .1       0
#XS Ineff= 2 , 0
        330.0601    1960
Permanent Ineff=
       F       F
Bank Sta=374.7,391.1
XS Rating Curve= 0 ,0
Exp/Cntr(USF)=0,0
Exp/Cntr=0.3,0.1

Type RM Length L Ch R = 1 ,64      ,,,
XS GIS Cut Line= 4
2293465.09402593727594.6781439442293747.29927316727425.634426425
2293771.96268263727210.5146882642293685.39467627726994.616501523
#Sta/Elev= 30
       0 1966.49    22.2 1959.13   117.1 1956.03   148.1 1956.63   181.2 1953.96
   204.1 1954.82   236.6 1954.37   265.8 1952.88   306.7 1953.12     329 1951.54
   349.6 1952.54   359.1  1951.9   385.8 1952.31   397.9 1951.37     414 1952.03
   423.71950.546   438.1  1949.7   452.21950.535   496.7    1953   522.7 1950.67
   530.7 1952.08   538.8 1956.38   551.2 1965.53   564.8 1974.18   598.6 1993.56
   633.1 2012.27   663.1 2025.91   680.5 2030.86   721.7 2038.81778.0974 2055.72
#Mann= 3 ,-1,0
       0      .1       0   423.7    .045       0   452.2      .1       0
Bank Sta=423.7,452.2
XS Rating Curve= 0 ,0
Exp/Cntr(USF)=0,0
Exp/Cntr=0.3,0.1
LCMann Table=0

Chan Stop Cuts=-1
Use User Specified Reach Order=0
Composite Channel Slope=5